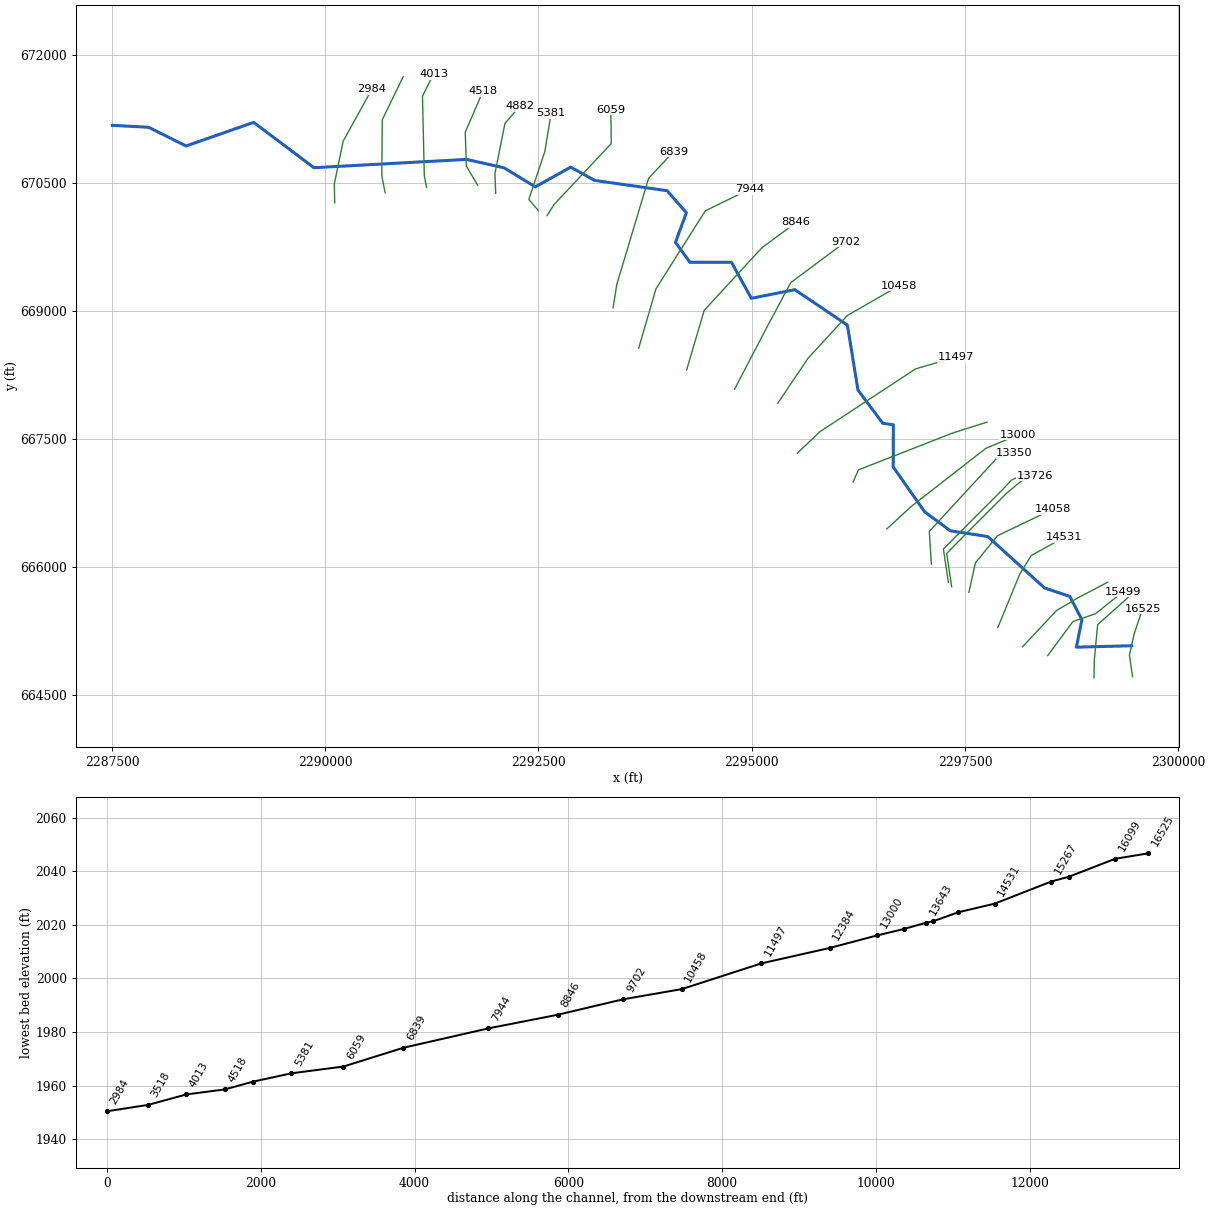
--- FILESCK.prj (project) ---

Proj Title=FILESCK
Current Plan=p01
Default Exp/Contr=0,0
English Units
Geom File=g01
Flow File=f01
Plan File=p01
BEGIN DESCRIPTION:
----------MODEL BY WOOD PLC 2022----------
AFH study
Randolph County, WV
HEC-RAS Version: RAS 6.2
Vertical Datum: NAVD88
Projection: NAD 1983 StatePlane West Virginia S FIPS 4702 (US Feet)
Terrain: 1-meter LIDAR (FEMA Region III 3DEP collected 2016-2018)
Land Use: 2019 NLCD
Hydrologic Method:
WV SIR2010-5033 regression equations
Additional Model Notes:
None
END DESCRIPTION:
DSS Export Rating Curves= 0
DSS Export Rating Curve Sorted= 0
DSS Export Volume Flow Curves= 0
DXF OffsetX= 0
DXF OffsetY= 0
DXF ScaleX= 0
DXF ScaleY= 0

--- FILESCK.p01 (plan) ---

Plan Title=Floodplain
Program Version=6.20
Short Identifier=Floodplain
Geom File=g01
Flow File=f01
Subcritical Flow
K Sum by GR= 0
Std Step Tol= 0.01
Critical Tol= 0.01
Num of Std Step Trials= 20
Max Error Tol= 0.3
Flow Tol Ratio= 0.001
Split Flow NTrial= 30
Split Flow Tol= 0.02
Split Flow Ratio= 0.02
Log Output Level= 0
Friction Slope Method= 1
Unsteady Friction Slope Method= 2
Unsteady Bridges Friction Slope Method= 1
Parabolic Critical Depth
Global Vel Dist= 0 , 0 , 0
Global Log Level= 0
CheckData=True
Encroach Param=-1 ,0,0, 0
Mapping Interval=1HOUR
Computation Time Step Use Courant=        0
Computation Time Step Use Time Series=    0
Computation Time Step Count To Double=0
Computation Time Step Max Doubling=0
Computation Time Step Max Halving=0
Computation Time Step Residence Courant=0
Run HTab= 0
Run UNet= 0
Run Sediment= 0
Run PostProcess= 0
Run WQNet= 0
Run RASMapper=-1
UNET Theta= 0
UNET Theta Warmup= 0
UNET ZTol= 0
UNET ZSATol= 0
UNET MxIter= 0
UNET Max Iter WO Improvement= 0
UNET MaxInSteps= 0
UNET DtIC= 0
UNET DtMin= 0
UNET MaxCRTS= 0
UNET WFStab= 0
UNET SFStab= 0
UNET WFX= 1
UNET SFX= 1
UNET Gravity=32.174
UNET 1D Methodology=Finite Difference
UNET DSS MLevel= 1
UNET Pardiso=0
UNET DZMax Abort= 0
UNET Use Existing IB Tables= 0
UNET Froude Reduction=False
UNET Froude Limit= 0
UNET Froude Power= 0
UNET D1 Cores= 0
UNET WindReference=Eulerian
UNET WindDragFormulation=Hsu (1988)
UNET D2 Coriolis=0
UNET D2 Cores= 0
UNET D2 Theta= 1
UNET D2 Theta Warmup= 1
UNET D2 Z Tol= 0.01
UNET D2 Volume Tol= 0.01
UNET D2 Max Iterations= 20
UNET D2 Equation= 0
UNET D2 RampUpFraction=0.1
UNET D2 TimeSlices= 1
UNET D2 Turbulence Formulation=Non-Conservative (original)
UNET D2 Eddy Viscosity=0.3
UNET D2 Transverse Eddy Viscosity=0.1
UNET D2 Smagorinsky Mixing=0
UNET D2 BCVolumeCheck=0
UNET D2 Cores=0
UNET D2 SolverType=PARDISO (Direct)
UNET D2 Minimum Iterations= 2147483647
UNET D2 Maximum Iterations= 2147483647
UNET D2 Restart Number= 10
UNET D2 Relaxation Coeff=1.3
UNET D2 SOR Precondition Iterations= 10
UNET D2 ILUT Maximum Fill= 8
UNET D2 ILUT Tolerance=1E-08
UNET D1D2 MaxIter= 0
UNET D1D2 ZTol=0.01
UNET D1D2 QTol=0.1
UNET D1D2 MinQTol=1
Write IC File= 0
Write IC File at Fixed DateTime=0
Write IC File at Sim End=0
Echo Input=False
Echo Parameters=False
Echo Output=False
Write Detailed= 0
HDF Write Warmup=0
HDF Write Time Slices=0
HDF Flush=0
HDF Compression= 1
HDF Chunk Size= 1
HDF Spatial Parts= 1
HDF Use Max Rows=0
HDF Fixed Rows= 1
Calibration Method= 0
Calibration Iterations= 20
Calibration Max Change=0.05
Calibration Tolerance=0.2
Calibration Maximum=1.5
Calibration Minimum=0.5
Calibration Optimization Method= 1
WQ AD Non Conservative
WQ ULTIMATE=-1
WQ Max Comp Step=1HOUR
WQ Output Interval=15MIN
WQ Output Selected Increments= 0
WQ Output face flow=0
WQ Output face velocity=0
WQ Output face area=0
WQ Output face dispersion=0
WQ Output cell volume=0
WQ Output cell surface area=0
WQ Output cell continuity=0
WQ Output cumulative cell continuity=0
WQ Output face conc=0
WQ Output face dconc_dx=0
WQ Output face courant=0
WQ Output face peclet=0
WQ Output face adv mass=0
WQ Output face disp mass=0
WQ Output cell mass=0
WQ Output cell source sink temp=0
WQ Output nsm pathways=0
WQ Output nsm derived pathways=0
WQ Create Restart=0
WQ Fixed Restart=0
WQ System Summary=0
WQ Write To DSS=0
Sorting and Armoring Iterations= 10
XS Update Threshold= 0.02
Bed Roughness Predictor= 0
Hydraulics Update Threshold= 0.02
Energy Slope Method= 1
Volume Change Method= 1
Sediment Retention Method= 0
Sediment TS Multiplier= 1
Warm Up Method= 0
XS Weighting Method= 0
Number of US Weighted Cross Sections= 1
Number of DS Weighted Cross Sections= 1
Upstream XS Weight=0
Main XS Weight=1
Downstream XS Weight=0
Number of DS XS's Weighted with US Boundary= 1
Upstream Boundary Weight= 1
Weight of XSs Associated with US Boundary= 0
Number of US XS's Weighted with DS Boundary= 1
Downstream Boundary Weight= 0.5
Weight of XSs Associated with DS Boundary= 0.5
Percentile Method= 0
Sediment Output Level= 3
Mass or Volume Output= 0
Output Increment Type= 1
Profile and TS Output Increment= 1
Transport Output Increment 1
XS Output Flag= 0
XS Output Increment= 10
Read HDF5 Sediment Hotstart= 0
Sediment Hotstart Type= 0
Write Gradation File= 0
Read Gradation Hotstart= 0
Write HDF5 File= 1
Write Binary Output= 1
Write DSS Sediment File= 0
DSS Sediment Output Type= 1
SV Curve= 0
Specific Gage Flag= 0
Subcell Erosion Methods= 0
Subcell Deposition Methods= 0
Advection Scheme= 1
Matrix Solver= 0
Implicit Weighting Factor= 1
Maximum Outer Loop Convergence Iterations= 5
Convergence Maximum Absolute= 0.001
Convergence RMSE= 0.0001
Grain Fractions Max Abs Error= 0.001
Max Subgrid Regions= 1
Max Subgrid Length Scale= 3.402823E+38
Initial Layer Thickness= 3.402823E+38
Min Layer Thickness= 3.402823E+38
Max Layer Thickness= 3.402823E+38
Number of Layers= 5

--- FILESCK.f01 (steady flow) ---

Flow Title=Flow
Program Version=6.20
Number of Profiles= 1
Profile Names=P100yr
River Rch & RM=FILESCK,Main,16525
    3380
Boundary for River Rch & Prof#=FILESCK,Main            , 1
Up Type= 0
Dn Type= 3
Dn Slope=0.00313
DSS Import GetInterval= 0
DSS Import GetPeak= 0
DSS Import FillOption= 0

--- FILESCK.g01 (geometry) ---

Geom Title=Geometry
Program Version=6.20

River Reach=FILESCK         ,Main
Reach XY= 30
     2299453.617      665072.527     2298806.232      665055.903
     2298870.505      665377.455     2298729.189      665650.293
     2298432.428       665750.39     2297767.172      666352.818
     2297328.499      666419.9432297026.84175731666642.816498875
      2296658.56      667168.887     2296660.009      667663.768
     2296536.382      667680.381     2296245.283      668070.367
2296121.43804897668832.029319643     2295505.482      669247.102
     2294995.111      669146.158     2294762.526      669568.271
     2294275.248      669569.264     2294105.842      669801.887
      2294233.97      670149.037     2294008.241      670407.975
     2293158.092      670528.514     2292877.512      670684.017
     2292462.928      670452.766     2292095.974       670676.41
2291655.69550849670774.8890169762289867.58518175670677.368545247
     2289160.225       671208.82     2288368.162      670932.301
     2287929.591      671151.432     2287505.637      671174.121

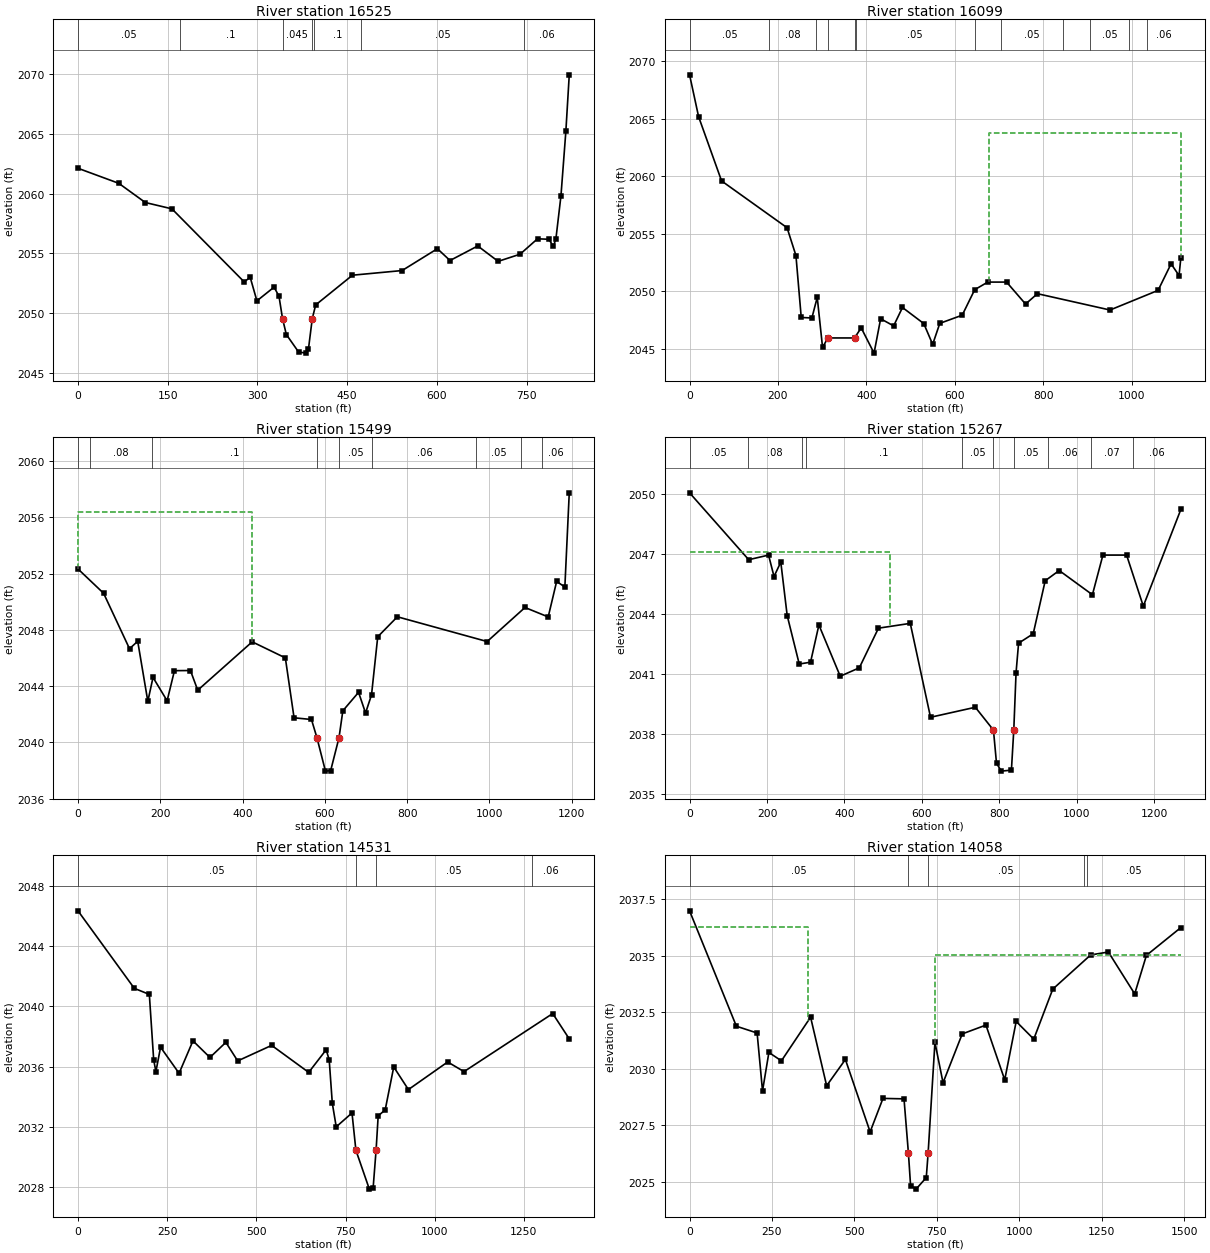
Type RM Length L Ch R = 1 ,16525   ,424.2,426.1,428.5
XS GIS Cut Line= 4
2299464.43829591664709.7186380242299427.75576398664961.101088313
2299482.21702256665206.7545874812299582.20352972665506.364958155
#Sta/Elev= 30
       0 2062.12    68.2 2060.86   112.6 2059.25   157.1 2058.72   277.9  2052.6
     288 2052.98   299.2 2051.01   327.9 2052.16   336.1  2051.4  342.022049.529
   348.4 2048.19   368.8 2046.73   381.1 2046.63   385.3 2046.94  391.782049.528
   397.5 2050.67     459 2053.16     542 2053.55     601 2055.38   622.1 2054.39
   668.5 2055.61   702.6 2054.32   739.3 2054.92   768.4 2056.21   787.4 2056.17
     795 2055.57   799.2 2056.22   807.6  2059.8   815.8 2065.21   821.5 2069.95
#Mann= 7 ,-1,0
       0     .05       0     170      .1       0  342.02    .045       0
  391.78     .05       0  394.04      .1       0  474.04     .05       0
  745.66     .06       0
Bank Sta=342.02,391.78
XS Rating Curve= 0 ,0
Exp/Cntr=0.3,0.1

Type RM Length L Ch R = 1 ,16099   ,633.6,599.5,567.4
XS GIS Cut Line= 4
2299012.20306973664696.8015904382299016.18685902664902.668590042
2299055.37703195665319.7931181072299418.07738539665643.889455659
#Sta/Elev= 30
       0 2068.84    20.4  2065.2    72.4 2059.61   220.5 2055.54   240.6 2053.12
   252.6 2047.73   276.7 2047.69   288.8 2049.48   300.8 2045.13   312.9 2045.95
   373.1 2045.95   388.2 2046.83   417.3 2044.63   432.2 2047.62   461.6    2047
   481.6  2048.6   529.8  2047.2   549.9 2045.39     566 2047.22   616.7 2047.93
     645 2050.15   674.6 2050.81   717.1 2050.81     760  2048.9   786.9  2049.8
   951.1 2048.38  1059.8 2050.09  1089.2  2052.4  1107.2 2051.38  1111.3 2052.92
#Mann= 12 ,-1,0
       0     .05       0     180     .08       0  285.91      .1       0
   312.9    .045       0   373.1      .1       0  375.91     .05       0
  644.87      .1       0  704.87     .05       0  844.87     .06       0
  904.87     .05       0  994.87     .07       0 1034.87     .06       0
#XS Ineff= 2 , 0
                          678.41         2063.74
Permanent Ineff=
       F       F
Bank Sta=312.9,373.1
XS Rating Curve= 0 ,0
Exp/Cntr=0.3,0.1

Type RM Length L Ch R = 1 ,15499   ,227.2,231.7,237.5
XS GIS Cut Line= 4
2298469.65726583 664956.619862672298764.50800666665355.380533049
2299030.74801421665448.8101712212299356.26361349665708.254069713
#Sta/Elev= 30
       0 2052.33    62.3  2050.6   125.3 2046.66   145.2 2047.19   169.8 2042.92
   182.4 2044.62   216.7 2042.96   234.5  2045.1   273.4 2045.11   291.1 2043.71
   423.5 2047.15   504.1 2046.01   525.3 2041.75   567.6 2041.63  580.84 2040.34
   601.6 2037.96   614.3    2038  634.582040.339   643.9 2042.25   682.1 2043.56
   699.1 2042.09   713.6 2043.38   728.7 2047.51   776.4 2048.93   994.7 2047.17
  1086.7 2049.59  1143.1 2048.92  1163.6 2051.44  1183.6 2051.05  1194.3 2057.74
#Mann= 9 ,-1,0
       0     .05       0      30     .08       0     180      .1       0
  580.84    .045       0  634.58     .05       0  715.93     .06       0
  968.09     .05       0 1078.09     .07       0 1128.09     .06       0
#XS Ineff= 2 , 0
          421.95 2056.41
Permanent Ineff=
       F       F
Bank Sta=580.84,634.58
XS Rating Curve= 0 ,0
Exp/Cntr=0.3,0.1

Type RM Length L Ch R = 1 ,15267   ,723.5,736.3,749.2
XS GIS Cut Line= 4
2298175.79267555665061.2300792222298574.80326817665487.115736619
2298835.72687616665640.6539328992299174.46801687665818.203693327
#Sta/Elev= 30
       0 2050.04   152.7  2046.7     204 2046.93   218.1 2045.86   235.6 2046.58
   252.1 2043.91   283.2 2041.49   312.4 2041.58     334 2043.44   389.1 2040.88
   438.4  2041.3   487.8 2043.28     570 2043.52   622.3 2038.83     738 2039.33
   784.8 2038.19   792.7 2036.53   805.2 2036.14   831.2 2036.19  837.32 2038.19
   843.2 2041.06   849.7 2042.53   887.5    2043   918.5 2045.65   954.6 2046.16
  1040.4 2044.95  1067.5 2046.93  1128.7 2046.93  1171.8 2044.38  1268.8 2049.21
#Mann= 10 ,-1,0
       0     .05       0     150     .08       0     290     .07       0
     300      .1       0   703.6     .05       0   784.8    .045       0
  837.32     .05       0  926.35     .06       0 1036.35     .07       0
 1146.35     .06       0
#XS Ineff= 2 , 0
          518.71  2047.1
Permanent Ineff=
       F       F
Bank Sta=784.8,837.32
XS Rating Curve= 0 ,0
Exp/Cntr=0.3,0.1

Type RM Length L Ch R = 1 ,14531   ,476.3,472.6,468.9
XS GIS Cut Line= 4
2297885.21012942665287.1122575122298143.30298241665914.375752263
2298276.50002174666129.5251547042298665.92789574666346.544337443
#Sta/Elev= 30
       0 2046.33   157.9 2041.19     200 2040.79   212.2 2036.45   218.4 2035.67
   231.5 2037.29   283.4 2035.56   322.3 2037.71   369.9 2036.61   414.5 2037.61
   447.7 2036.38   542.9 2037.41   646.7 2035.62   695.7 2037.12   704.2 2036.45
   712.9 2033.57   723.9 2032.01   768.1 2032.93  778.992030.462   816.7 2027.88
   827.4 2027.98  835.622030.461   841.5 2032.74   861.1 2033.13   885.1 2035.98
   926.2 2034.48  1036.3 2036.31  1082.1 2035.67  1330.7 2039.52  1377.1 2037.84
#Mann= 4 ,-1,0
       0     .05       0  778.99    .045       0  835.62     .05       0
 1271.33     .06       0
Bank Sta=778.99,835.62
XS Rating Curve= 0 ,0
Exp/Cntr=0.3,0.1

Type RM Length L Ch R = 1 ,14058   ,346.9,332.6,332.6
XS GIS Cut Line= 4
2297545.75106922665697.0285286262297621.84835225666043.878986617
2297881.24711093666362.0753274482298534.37421714 666676.07983066
#Sta/Elev= 30
       0 2036.98     142 2031.88   204.9 2031.58   221.3 2029.02   240.6 2030.72
   278.6 2030.35   367.1 2032.28   415.8 2029.25   472.7 2030.41   547.7 2027.21
   586.7 2028.69   650.5 2028.67  663.94 2026.26   670.4 2024.84   687.1 2024.68
     718 2025.19   723.62026.259   744.3 2031.17   768.9 2029.38   827.1 2031.54
     899 2031.93     956 2029.51   990.8 2032.09  1044.1 2031.31  1101.8 2033.52
  1216.7 2035.03  1270.4 2035.16  1350.3 2033.31  1385.8 2035.01  1490.3 2036.24
#Mann= 5 ,-1,0
       0     .05       0  663.94    .045       0   723.6     .05       0
 1195.63      .1       0 1205.63     .05       0
#XS Ineff= 2 , 0
          359.28 2036.26  745.13         2035.02
Permanent Ineff=
       F       F
Bank Sta=663.94,723.6
XS Rating Curve= 0 ,0
Exp/Cntr=0.3,0.1

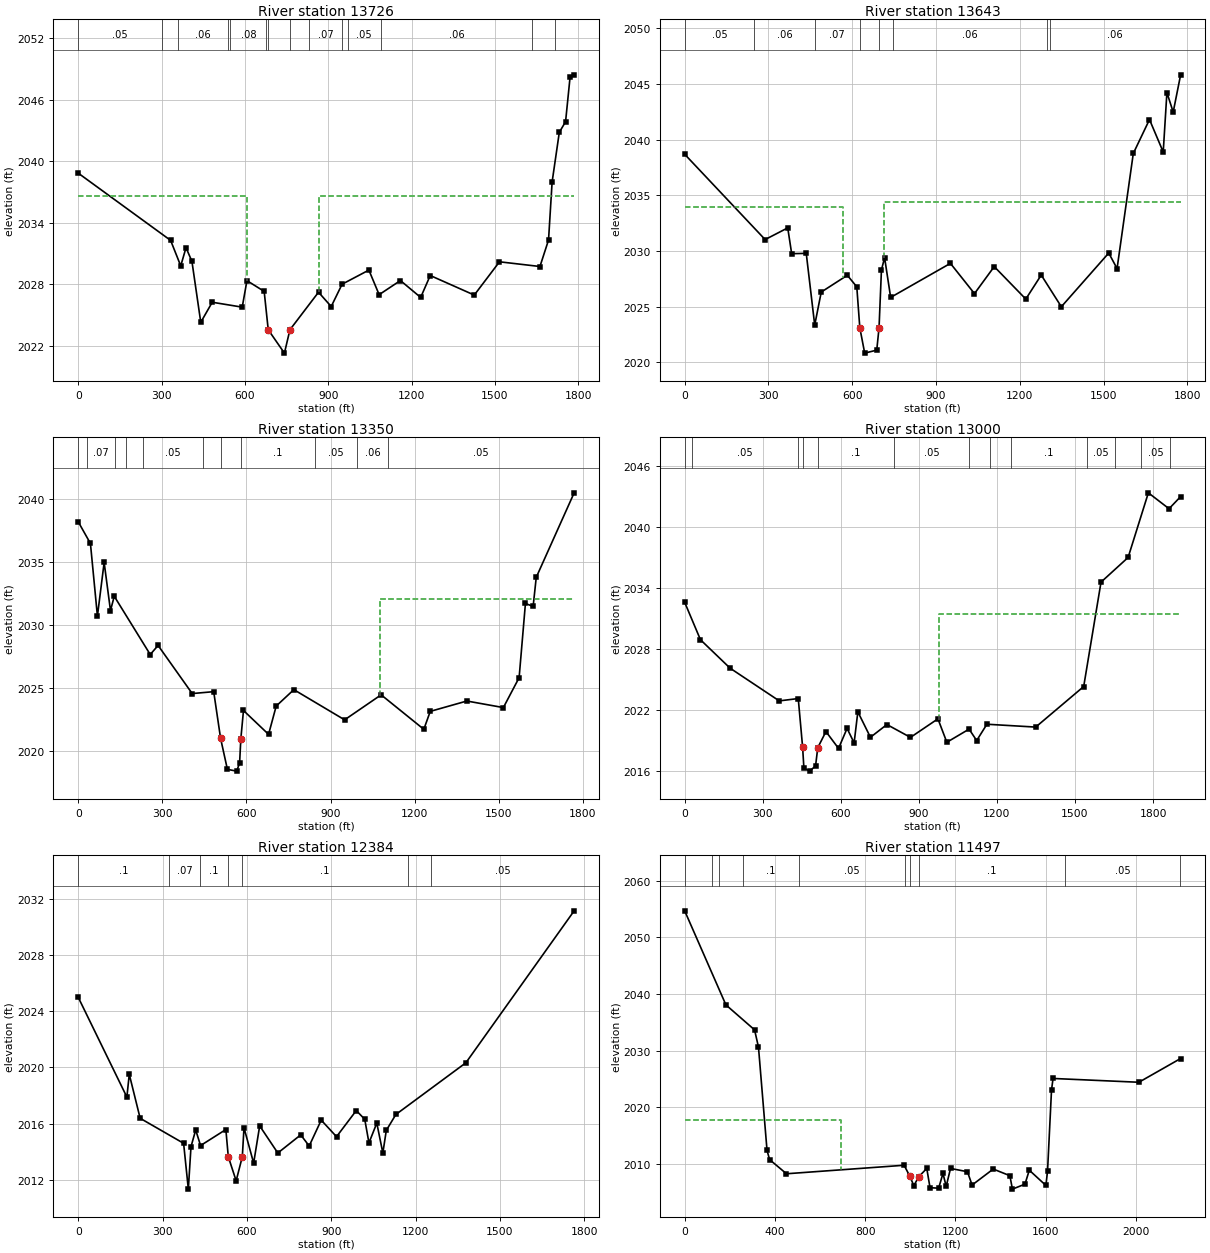
Type RM Length L Ch R = 1 ,13726   ,79.2,82.8,85
XS GIS Cut Line= 6
2297343.76872336665764.1417743512297285.59065175666155.303563081
2297675.64791964666549.0233405282297986.77842909666859.583592857
2298159.76357729667003.9765695542298317.66056879667068.026363319
#Sta/Elev= 30
       0 2038.85   332.6 2032.28     369 2029.79     388 2031.57   409.3 2030.23
   441.1 2024.28   482.4 2026.24   590.3 2025.76   607.3 2028.35   669.3  2027.3
  683.932023.551   742.2 2021.27  761.992023.552   864.9 2027.22   910.6 2025.82
   949.7    2028  1046.2 2029.38  1083.1 2026.98  1159.7 2028.36  1232.6 2026.71
    1267 2028.85  1425.5 2026.94  1516.2 2030.19  1661.9 2029.73  1692.8 2032.32
  1705.7 2037.99  1731.6 2042.84  1754.1 2043.87  1770.5 2048.28    1785 2048.45
#Mann= 14 ,-1,0
       0     .05       0     300     .07       0     360     .06       0
  538.06     .07       0  548.06     .08       0  677.26     .07       0
  683.93    .045       0  761.99     .06       0  831.36     .07       0
   949.7     .06       0   969.7     .05       0 1088.39     .06       0
 1634.64     .05       0 1714.64     .06       0
#XS Ineff= 2 , 0
          608.13 2036.64  865.12         2036.64
Permanent Ineff=
       F       F
Bank Sta=683.93,761.99
XS Rating Curve= 0 ,0
Exp/Cntr(USF)=0,0
Exp/Cntr=0.3,0.1

Type RM Length L Ch R = 1 ,13643   ,290.9,293.5,297.6
XS GIS Cut Line= 6
2297305.05416608665814.8711942342297246.87609447666206.032982964
2297636.93336236666599.7527604112297948.06387181 666910.31301274
2298041.47734209667012.5017036222298264.02702689667123.018350237
#Sta/Elev= 30
       0 2038.69   288.1 2031.02   369.1 2032.07   383.2 2029.75   435.4 2029.78
   465.7 2023.33   489.1  2026.3   582.5 2027.81   616.4 2026.77  627.212023.097
   644.7 2020.81   687.9 2021.08  696.132023.098   704.7 2028.29     716 2029.39
   737.7 2025.82   951.7 2028.88  1037.9 2026.16  1108.6 2028.59  1221.7 2025.67
    1277 2027.83    1349 2024.98  1518.8 2029.81  1548.6 2028.41  1606.7 2038.76
  1664.7 2041.81  1713.9 2038.89  1727.1 2044.24  1749.6 2042.48  1776.2 2045.83
#Mann= 8 ,-1,0
       0     .05       0     250     .06       0  465.47     .07       0
  627.21    .045       0  696.13     .07       0  747.26     .06       0
 1297.29      .1       0 1307.29     .06       0
#XS Ineff= 2 , 0
          565.85 2033.94  715.45         2034.44
Permanent Ineff=
       F       F
Bank Sta=627.21,696.13
XS Rating Curve= 0 ,0
Exp/Cntr(USF)=0,0
Exp/Cntr=0.3,0.1

Type RM Length L Ch R = 1 ,13350   ,350.8,349.3,341
XS GIS Cut Line= 4
     2297106.106      666028.8422297081.39840392666412.844076739
2297872.72255887667271.2592710512298080.46302516667332.929123891
#Sta/Elev= 30
       0 2038.16    43.6 2036.44    68.5 2030.69    92.5 2034.94   115.1 2031.13
   128.6 2032.26   256.9 2027.65   284.9 2028.37   406.6 2024.56   483.3 2024.71
   507.82021.021   532.1 2018.56   565.3 2018.42   575.7 2019.07     5802020.965
   589.5 2023.22     679 2021.33   706.2 2023.57   769.2 2024.87   950.3 2022.48
  1080.5 2024.46  1232.8 2021.73  1255.7 2023.15  1386.3 2023.97  1516.5 2023.45
  1572.7 2025.82  1595.2 2031.69  1622.7 2031.46  1633.8 2033.76    1769 2040.45
#Mann= 11 ,-1,0
       0     .05       0      30     .07       0     130     .05       0
     170      .1       0     230     .05       0   444.8      .1       0
   507.8    .045       0     580      .1       0   844.8     .05       0
   994.8     .06       0  1104.8     .05       0
#XS Ineff= 2 , 0
                         1076.42         2032.05
Permanent Ineff=
       F       F
Bank Sta=507.8,580
XS Rating Curve= 0 ,0
Exp/Cntr=0.3,0.1

Type RM Length L Ch R = 1 ,13000   ,622.2,616.3,606.9
XS GIS Cut Line= 4
2296584.60388001666443.0828399522296874.60209864666709.649902417
 2297743.2855349667386.2874440482298122.21958289667545.412802727
#Sta/Elev= 30
       0 2032.58    60.6 2028.91   174.5 2026.12   363.5 2022.91   436.5 2023.14
  453.06 2018.43   458.2 2016.32   480.2 2016.02     503 2016.53   511.5 2018.32
   542.9  2019.9   591.3 2018.25   624.1 2020.21   651.2 2018.79   665.5 2021.84
   713.9 2019.34   777.2 2020.59   867.8 2019.33   973.3 2021.15  1007.5 2018.85
    1093 2020.14  1122.2 2019.02  1161.5 2020.62  1349.1 2020.34  1533.5 2024.32
  1600.1 2034.56  1704.2 2036.98    1782 2043.32  1861.5 2041.76    1906 2042.95
#Mann= 13 ,-1,0
       0      .1       0      30     .05       0   433.9      .1       0
  453.06    .045       0   511.5      .1       0   803.9     .05       0
  1093.9      .1       0  1173.9     .05       0  1253.9      .1       0
 1545.01     .05       0 1655.01      .1       0 1755.01     .05       0
 1865.01      .1       0
#XS Ineff= 2 , 0
                          975.61         2031.46
Permanent Ineff=
       F       F
Bank Sta=453.06,511.5
XS Rating Curve= 0 ,0
Exp/Cntr=0.3,0.1

Type RM Length L Ch R = 1 ,12384   ,871.2,887.2,876.9
XS GIS Cut Line= 4
2296189.53521863666993.2999219182296250.04946013667134.473054657
2297354.43835997667566.3676485262297759.33869658667694.492742881
#Sta/Elev= 30
       0 2024.99   173.1 2017.89   181.6 2019.51   220.3 2016.38   374.9  2014.6
   391.7 2011.34   401.2 2014.36   417.9 2015.55   435.2 2014.44   525.2 2015.58
   533.8 2013.65   561.8 2011.93  583.782013.653   589.7 2015.71     624 2013.19
   645.5 2015.84     710 2013.91   791.5  2015.2   821.6 2014.41   864.4 2016.25
   918.8 2015.07   989.1 2016.93  1019.2 2016.31  1034.2 2014.63  1062.1 2016.04
  1083.6 2013.91  1095.9 2015.52  1129.9 2016.65    1379 2020.33  1764.1 2031.14
#Mann= 7 ,-1,0
       0      .1       0   323.6     .07       0   433.6      .1       0
   533.8    .045       0  583.78      .1       0  1173.6     .07       0
  1253.6     .05       0
Bank Sta=533.8,583.78
XS Rating Curve= 0 ,0
Exp/Cntr=0.3,0.1

Type RM Length L Ch R = 1 ,11497   ,1027.5,1038.6,1031.9
XS GIS Cut Line= 4
2295535.52438059667331.2899179052295801.07270899667583.603555119
2296921.85640028668319.0436168652297393.99455813668456.840571951
#Sta/Elev= 30
       0 2054.69   182.8  2038.1   309.9 2033.69   327.2 2030.64   365.1 2012.42
   376.5 2010.81   451.3 2008.31   972.8 2009.81  998.472007.852  1015.9 2006.22
 1038.392007.812  1073.3 2009.25  1087.7 2005.85  1125.9 2005.77  1145.1 2008.36
  1159.4 2006.09  1178.6 2009.25  1253.6 2008.67  1274.2 2006.32    1368 2009.14
  1441.7 2007.97    1453  2005.6  1508.7 2006.48  1527.8 2008.94  1601.4 2006.25
  1608.7 2008.76  1626.3 2023.06  1633.1 2025.12  2013.6 2024.45  2198.7 2028.64
#Mann= 10 ,-1,0
       0     .05       0     120      .1       0     150     .05       0
     260      .1       0   506.3     .05       0   976.3      .1       0
  998.47    .045       0 1038.39      .1       0  1686.3     .05       0
 2196.84      .1       0
#XS Ineff= 2 , 0
          691.34 2017.84
Permanent Ineff=
       F       F
Bank Sta=998.47,1038.39
XS Rating Curve= 0 ,0
Exp/Cntr=0.3,0.1

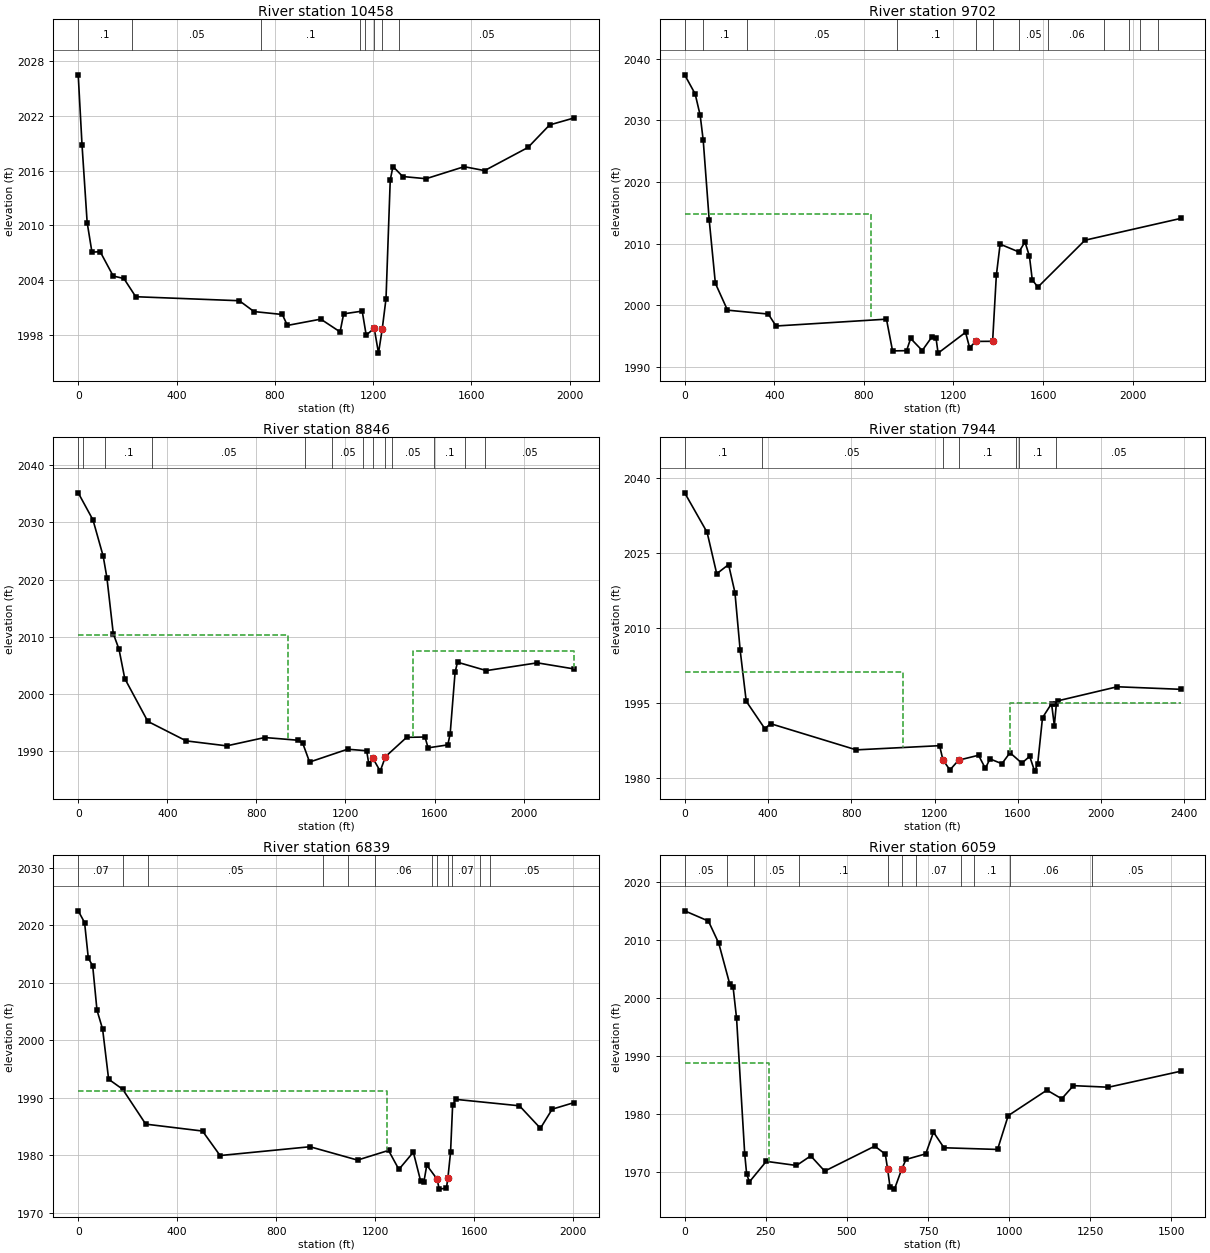
Type RM Length L Ch R = 1 ,10458   ,750.6,756.6,760.7
XS GIS Cut Line= 4
2295304.84603588667914.9766906052295659.37839263668442.625545516
2296120.99274161668944.4805507782296728.14407158669293.630228632
#Sta/Elev= 30
       0 2026.52    15.5 2018.83    36.4 2010.31    55.9 2007.06    89.4 2007.11
   142.4 2004.44   185.8 2004.17     234 2002.17   655.5 2001.73   715.3 2000.54
   830.6 2000.22   851.1 1999.02     987 1999.71  1065.5 1998.31    1080 2000.29
  1155.5 2000.59  1171.8 1997.95  1204.4 1998.71  1221.8 1995.98    1237 1998.63
  1252.4 2001.96  1269.6 2014.98  1280.7 2016.46  1320.4 2015.36  1415.3 2015.12
  1570.4 2016.44  1653.5 2016.01  1830.1 2018.55    1918 2021.02  2017.9 2021.79
#Mann= 8 ,-1,0
       0      .1       0     220     .05       0  745.69      .1       0
 1145.69     .05       0 1165.69      .1       0  1204.4    .045       0
    1237      .1       0 1305.69     .05       0
Bank Sta=1204.4,1237
XS Rating Curve= 0 ,0
Exp/Cntr=0.3,0.1

Type RM Length L Ch R = 1 ,9702    ,831.5,855.3,828.4
XS GIS Cut Line= 4
  2294797.957921668079.7345299772295189.53940609 668829.84534307
2295457.85309024669330.4651912442296099.34607961669808.211515831
#Sta/Elev= 30
       0 2037.37    46.8 2034.27    69.3 2030.78    82.8 2026.73   109.4 2013.85
     137 2003.55   191.1 1999.19   373.3 1998.56   407.7 1996.62   900.8 1997.73
     928 1992.58   990.6 1992.62  1008.8  1994.6  1060.4 1992.64  1104.1 1994.87
  1122.2 1994.62  1131.3 1992.22  1253.9 1995.59    1272  1993.1  1299.2 1994.12
  1374.71994.139  1391.3 2004.82  1408.2  2009.9  1492.1 2008.63  1519.2 2010.26
  1539.2 2007.92  1551.7 2004.11  1576.7 2002.93    1787 2010.54    2214 2014.07
#Mann= 12 ,-1,0
       0     .05       0      80      .1       0     280     .05       0
  946.17      .1       0  1299.2    .045       0  1374.7      .1       0
 1494.16     .05       0 1624.16     .06       0 1874.16     .07       0
 1984.16     .05       0 2034.16     .06       0 2114.16     .05       0
#XS Ineff= 2 , 0
          833.93 2014.85
Permanent Ineff=
       F       F
Bank Sta=1299.2,1374.7
XS Rating Curve= 0 ,0
Exp/Cntr=0.3,0.1

Type RM Length L Ch R = 1 ,8846    ,871.5,902,880.7
XS GIS Cut Line= 4
2294236.32109315668305.4821392612294442.77873348669005.053905628
2295119.16917651669739.0985866412295521.14117245670035.581625575
#Sta/Elev= 30
       0  2035.2    66.4 2030.44   112.3 2024.07     129 2020.28   157.4 2010.53
   183.2 2007.78     209 2002.65   312.5 1995.14   484.9 1991.72     667 1990.85
   837.7 1992.31   985.3 1991.84  1007.9 1991.34    1039 1988.01  1209.6 1990.26
  1295.3 1989.99  1305.1 1987.62  1322.1 1988.75  1356.1 1986.42  1379.81988.958
  1474.7 1992.34  1557.1  1992.4  1571.2  1990.5  1659.7 1991.02  1670.3 1992.99
  1692.3 2003.75  1703.2 2005.51  1832.7 2004.04  2061.6  2005.4    2227 2004.33
#Mann= 13 ,-1,0
       0     .08       0      20     .05       0     120      .1       0
     330     .05       0  1019.4     .07       0  1139.4     .05       0
  1279.4      .1       0  1322.1    .045       0  1379.8      .1       0
  1409.4     .05       0  1599.4      .1       0 1737.56     .06       0
 1827.56     .05       0
#XS Ineff= 2 , 0
          942.24 2010.35 1501.81         2007.51
Permanent Ineff=
       F       F
Bank Sta=1322.1,1379.8
XS Rating Curve= 0 ,0
Exp/Cntr=0.3,0.1

Type RM Length L Ch R = 1 ,7944    ,1101.7,1105.3,1093.2
XS GIS Cut Line= 4
2293674.55073949668561.3683997982293876.62043683669256.201599859
2294455.08562549670171.0726922462294972.26733384670424.352386103
#Sta/Elev= 30
       0 2037.09   107.7 2029.18   153.9 2020.88   210.9 2022.72   241.4 2017.11
   266.4 2005.58   295.6 1995.34   385.2 1989.83   412.2 1990.85   824.2  1985.6
  1224.3 1986.44  1240.1 1983.63  1273.7 1981.57  1315.5 1983.53  1411.4 1984.52
  1444.1 1981.89  1466.2 1983.79  1523.6 1982.82  1562.4 1985.03  1619.2 1982.94
  1657.1  1984.3  1680.6 1981.34  1695.3 1982.74  1718.6 1992.05    1762 1994.87
  1775.4 1990.46  1784.9 1994.71  1790.9 1995.41  2077.5 1998.24  2381.9 1997.73
#Mann= 7 ,-1,0
       0      .1       0     370     .05       0  1240.1    .045       0
  1315.5      .1       0 1593.62     .05       0 1603.62      .1       0
 1783.62     .05       0
#XS Ineff= 2 , 0
         1046.93 2001.12 1560.31         1995.03
Permanent Ineff=
       F       F
Bank Sta=1240.1,1315.5
XS Rating Curve= 0 ,0
Exp/Cntr=0.3,0.1

Type RM Length L Ch R = 1 ,6839    ,790.4,780.5,770.6
XS GIS Cut Line= 4
2293374.62974285669035.8452422912293419.01988964669313.141357215
2293790.94986239670552.9803644082294083.75343775 670865.98290624
#Sta/Elev= 30
       0  2022.5    25.7 2020.46    40.9 2014.24    58.4 2012.97    75.8 2005.23
    98.6 2001.93   122.9 1993.22   179.6 1991.48   272.8 1985.41   502.2 1984.21
   573.2 1979.95   936.5 1981.48  1128.6 1979.16  1253.9 1980.84  1295.7 1977.54
  1354.1 1980.54  1383.6 1975.52  1396.5 1975.29  1408.4 1978.28  1450.2 1975.84
  1458.5 1974.11  1487.8 1974.28 1493.731976.049  1504.5 1980.52  1512.8 1988.66
  1525.3 1989.72  1782.8  1988.6  1867.7 1984.69  1915.1 1988.01  2003.9 1989.16
#Mann= 12 ,-1,0
       0     .07       0     180     .06       0     280     .05       0
  990.83     .06       0 1090.83     .05       0 1200.83     .06       0
 1430.83      .1       0  1450.2    .045       0 1493.73      .1       0
 1510.83     .07       0 1625.25     .06       0 1665.25     .05       0
#XS Ineff= 2 , 0
         1248.45 1991.09
Permanent Ineff=
       F       F
Bank Sta=1450.2,1493.73
XS Rating Curve= 0 ,0
Exp/Cntr=0.3,0.1

Type RM Length L Ch R = 1 ,6059    ,666.4,677.2,684.3
XS GIS Cut Line= 4
2292600.42382219670116.1148912262292681.95387799670244.999483737
2293353.02093696670960.9274530492293347.85087813 671355.56064771
#Sta/Elev= 30
       0    2015    73.1 2013.24     105 2009.42   138.5 2002.47   149.2 2001.88
   159.9 1996.51     185 1973.18     191 1969.69   199.5 1968.35   251.4 1971.88
   344.6 1971.17   388.5 1972.82   431.5  1970.2   585.9  1974.5   618.3 1973.12
  625.43 1970.55   632.8 1967.47   646.6  1967.1   669.2 1970.59   682.2 1972.21
   742.8 1973.17   766.8  1976.9   799.1 1974.22   964.2 1973.93   997.1 1979.75
  1116.4 1984.14    1162 1982.65    1198 1984.91    1306 1984.64  1528.4 1987.39
#Mann= 11 ,-1,0
       0     .05       0     130      .1       0  212.51     .05       0
  352.51      .1       0  625.43    .045       0   669.2      .1       0
  712.51     .07       0  852.51     .05       0  892.51      .1       0
 1002.51     .06       0 1253.77     .05       0
#XS Ineff= 2 , 0
          260.16 1988.88
Permanent Ineff=
       F       F
Bank Sta=625.43,669.2
XS Rating Curve= 0 ,0
Exp/Cntr=0.3,0.1

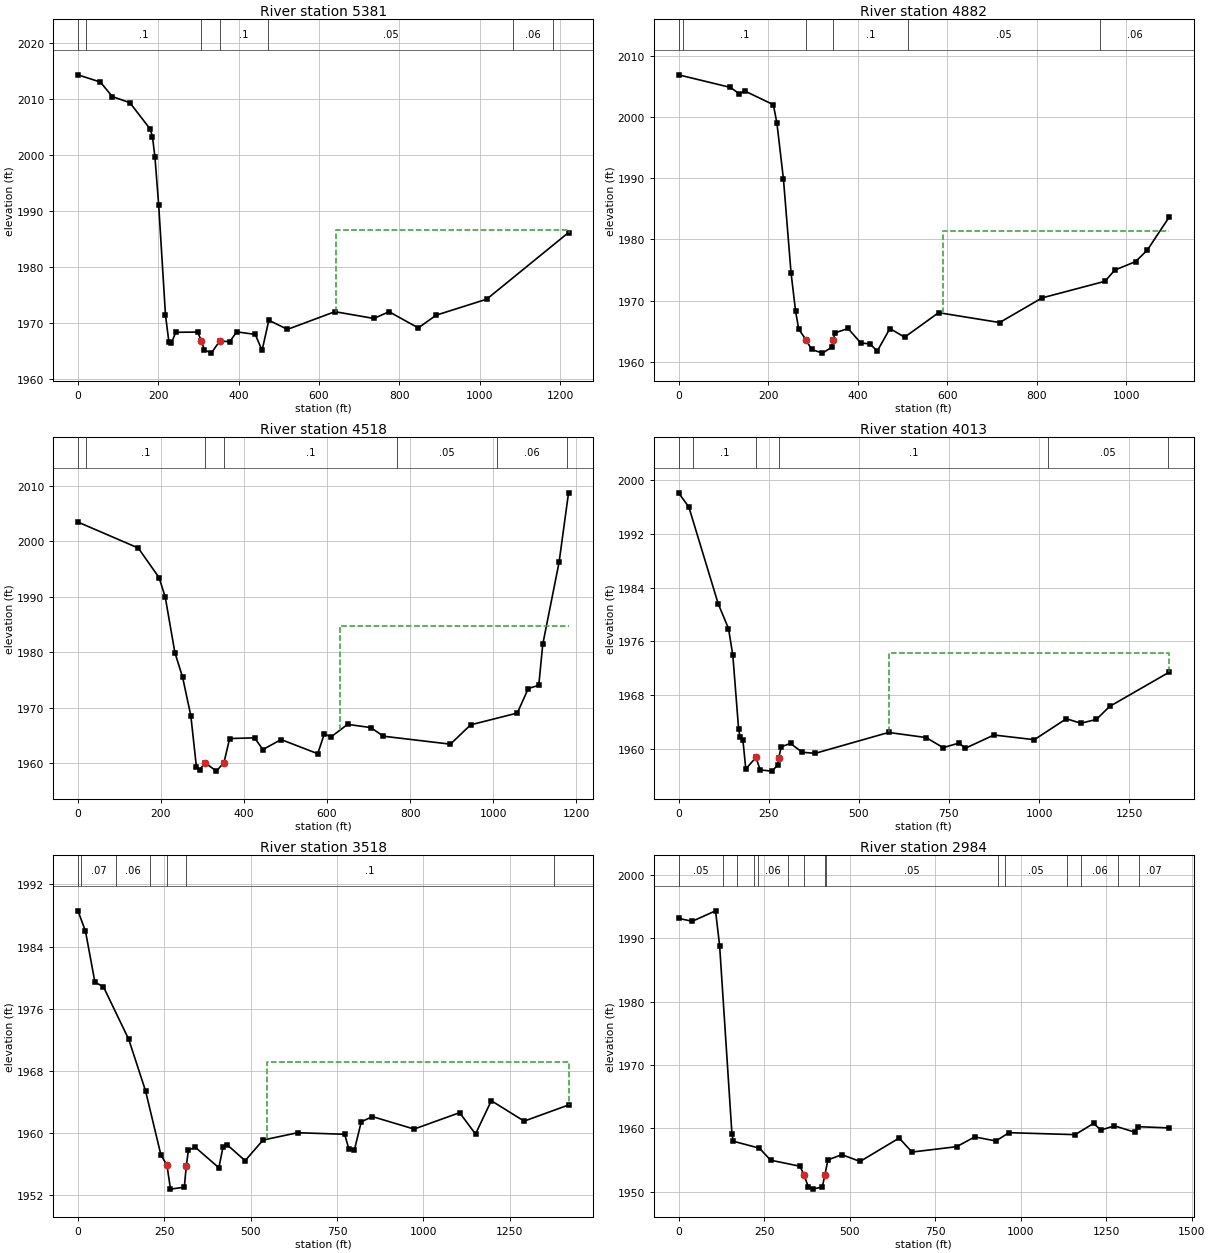
Type RM Length L Ch R = 1 ,5381    ,490.1,499.5,500.9
XS GIS Cut Line= 4
 2292498.6274374670174.8415842792292386.85479084 670305.81219225
2292574.07917859670866.5068202642292648.75140463671318.129951575
#Sta/Elev= 30
       0 2014.26    55.7 2012.97    85.7 2010.37   129.3 2009.28   179.9 2004.57
   185.4 2003.24   191.7 1999.52     201 1990.97   217.9 1971.36   226.3 1966.59
   232.8 1966.35   243.2 1968.29     298 1968.33  307.28 1966.72   314.7 1965.16
   331.8 1964.57   352.8 1966.71   378.2 1966.63     395 1968.37   441.4 1967.91
   458.3 1965.05   475.1 1970.44   521.5 1968.81   639.6 1971.97   736.6 1970.76
   774.4 1971.96   847.1 1969.07   891.7 1971.35  1017.4  1974.2  1221.1  1986.1
#Mann= 7 ,-1,0
       0     .05       0      20      .1       0  307.28    .045       0
   352.8      .1       0  472.18     .05       0 1083.31     .06       0
 1183.31     .05       0
#XS Ineff= 2 , 0
                          641.95         1986.63
Permanent Ineff=
       F       F
Bank Sta=307.28,352.8
XS Rating Curve= 0 ,0
Exp/Cntr=0.3,0.1

Type RM Length L Ch R = 1 ,4882    ,356.7,364.3,367
XS GIS Cut Line= 4
2291997.97214079670377.5083439892291989.49892161670610.885515524
2292106.91729143671196.5526897972292278.99722894671398.144980524
#Sta/Elev= 30
       0 2006.86   115.7 2004.81   135.8 2003.77   147.8 2004.23   211.8 2001.99
   219.8 1998.97   234.4 1989.83   251.3 1974.59   261.5 1968.28   268.5 1965.37
  285.511963.555   297.1 1962.06   321.5 1961.46   341.9 1962.41  345.051963.543
   350.1 1964.78   378.7 1965.48   407.2 1963.11   427.6 1962.97   443.9 1961.79
   472.2 1965.47   505.1 1964.06     581 1968.06   717.3 1966.45   812.1 1970.47
   952.6 1973.18   974.5 1975.01    1021 1976.39  1047.3 1978.28  1095.9 1983.64
#Mann= 6 ,-1,0
       0     .05       0      10      .1       0  285.51    .045       0
  345.05      .1       0  513.53     .05       0  940.85     .06       0
#XS Ineff= 2 , 0
                          591.77         1981.45
Permanent Ineff=
       F       F
Bank Sta=285.51,345.05
XS Rating Curve= 0 ,0
Exp/Cntr=0.3,0.1

Type RM Length L Ch R = 1 ,4518    ,504,504.5,503
XS GIS Cut Line= 4
2291786.55072801670472.0196623222291653.96644416670697.007478301
2291641.48531786671094.8484600262291849.62650068671574.146382555
#Sta/Elev= 30
       0 2003.47   145.3 1998.79   195.4 1993.46   210.3 1989.94   233.5 1979.95
   252.1  1975.5   271.9 1968.57   285.3 1959.37   293.3 1958.79   305.7 1960.12
   333.4 1958.58  351.711960.125   365.4 1964.45   425.4 1964.58   445.4 1962.47
   489.4 1964.27   577.5 1961.72   593.5 1965.29   609.5 1964.74   649.5 1967.01
   705.3 1966.43   735.9 1964.87   897.2 1963.44   945.8 1966.92  1058.3 1969.05
  1084.7 1973.47    1110 1974.05  1119.6 1981.44  1158.9 1996.21  1181.7 2008.74
#Mann= 7 ,-1,0
       0     .05       0      20      .1       0   305.7    .045       0
  351.71      .1       0  769.18     .05       0 1009.18     .06       0
 1179.18      .1       0
#XS Ineff= 2 , 0
                          631.62         1984.79
Permanent Ineff=
       F       F
Bank Sta=305.7,351.71
XS Rating Curve= 0 ,0
Exp/Cntr=0.3,0.1

Type RM Length L Ch R = 1 ,4013    ,496.4,495.3,494.9
XS GIS Cut Line= 4
2291187.66069369670449.1522972632291161.46410631670582.486733221
2291139.69840175671513.4347210542291269.29428834671776.998509416
#Sta/Elev= 30
       0 1998.13    28.6 1996.02   110.1  1981.6   138.6 1977.92   150.6 1973.94
   166.6 1962.98   170.6 1961.79   178.6 1961.28   186.6    1957   214.6 1958.71
   226.6 1956.86   258.6 1956.68   274.6 1957.53  277.931958.621   284.8 1960.31
   310.6  1960.8   343.1 1959.49     379 1959.33   582.7 1962.44   686.7 1961.68
     734 1960.18   778.8 1960.87   794.8 1960.07   874.8 1962.06   986.8 1961.36
  1075.7 1964.48  1115.8 1963.82  1158.8 1964.37  1195.7 1966.31  1360.8 1971.41
#Mann= 6 ,-1,0
       0     .05       0      40      .1       0   214.6    .045       0
  277.93      .1       0 1025.88     .05       0 1357.09     .07       0
#XS Ineff= 2 , 0
                          582.76         1974.21
Permanent Ineff=
       F       F
Bank Sta=214.6,277.93
XS Rating Curve= 0 ,0
Exp/Cntr=0.3,0.1

Type RM Length L Ch R = 1 ,3518    ,538.8,533.8,529.7
XS GIS Cut Line= 4
 2290701.4509063670384.9194300022290663.27898438670581.195335752
2290668.38163099671239.603278274 2290913.8284471671744.866715787
#Sta/Elev= 30
       0 1988.61    21.8 1985.99    49.2 1979.41    73.6 1978.85     147 1972.07
   195.8 1965.42   239.9 1957.23  257.681955.868   267.9 1952.79   307.9 1953.04
  313.671955.788   319.9 1957.84   340.1 1958.16   407.9 1955.54   419.9 1958.21
   431.9  1958.5   483.9 1956.45   535.9 1959.11     636 1960.05     772 1959.85
     784    1958   800.2 1957.82     820 1961.44     852 1962.13   973.1 1960.52
  1104.8 1962.63  1150.8 1959.88  1196.6 1964.17  1291.5 1961.54  1420.1 1963.62
#Mann= 7 ,-1,0
       0     .06       0      10     .07       0     110     .06       0
  209.95      .1       0  257.68    .045       0  313.67      .1       0
 1378.38     .06       0
#XS Ineff= 2 , 0
                          546.34         1969.19
Permanent Ineff=
       F       F
Bank Sta=257.68,313.67
XS Rating Curve= 0 ,0
Exp/Cntr=0.3,0.1

Type RM Length L Ch R = 1 ,2984    ,611.6,590.7,576.3
XS GIS Cut Line= 4
2290111.12474604670265.0203677452290105.94759677670486.044053545
2290210.29325167670989.3241849582290548.60588377671601.065195818
#Sta/Elev= 30
       0 1993.16    40.2  1992.7   108.2 1994.35   120.1 1988.86   156.2 1959.08
   160.2 1957.98   236.5 1956.88   269.2 1954.99     355 1954.03  367.391952.607
   379.5 1950.74   391.8 1950.42   420.4 1950.76  427.521952.609   436.7 1955.04
   477.6 1955.86   530.7 1954.79     645 1958.48   682.4 1956.27   812.9 1957.12
   865.8 1958.66   927.7 1958.02   965.9 1959.33  1159.4 1959.02  1213.1 1960.79
  1234.9 1959.75  1274.3 1960.41  1333.7 1959.41  1342.8 1960.28  1434.1 1960.08
#Mann= 15 ,-1,0
       0     .05       0     130     .06       0     170     .07       0
  221.08     .05       0  231.08     .06       0  321.08      .1       0
  367.39    .045       0  427.52      .1       0  431.08     .05       0
  935.07      .1       0  955.07     .05       0 1135.07      .1       0
 1175.07     .06       0 1285.07     .08       0 1345.07     .07       0
Bank Sta=367.39,427.52
XS Rating Curve= 0 ,0
Exp/Cntr=0.3,0.1