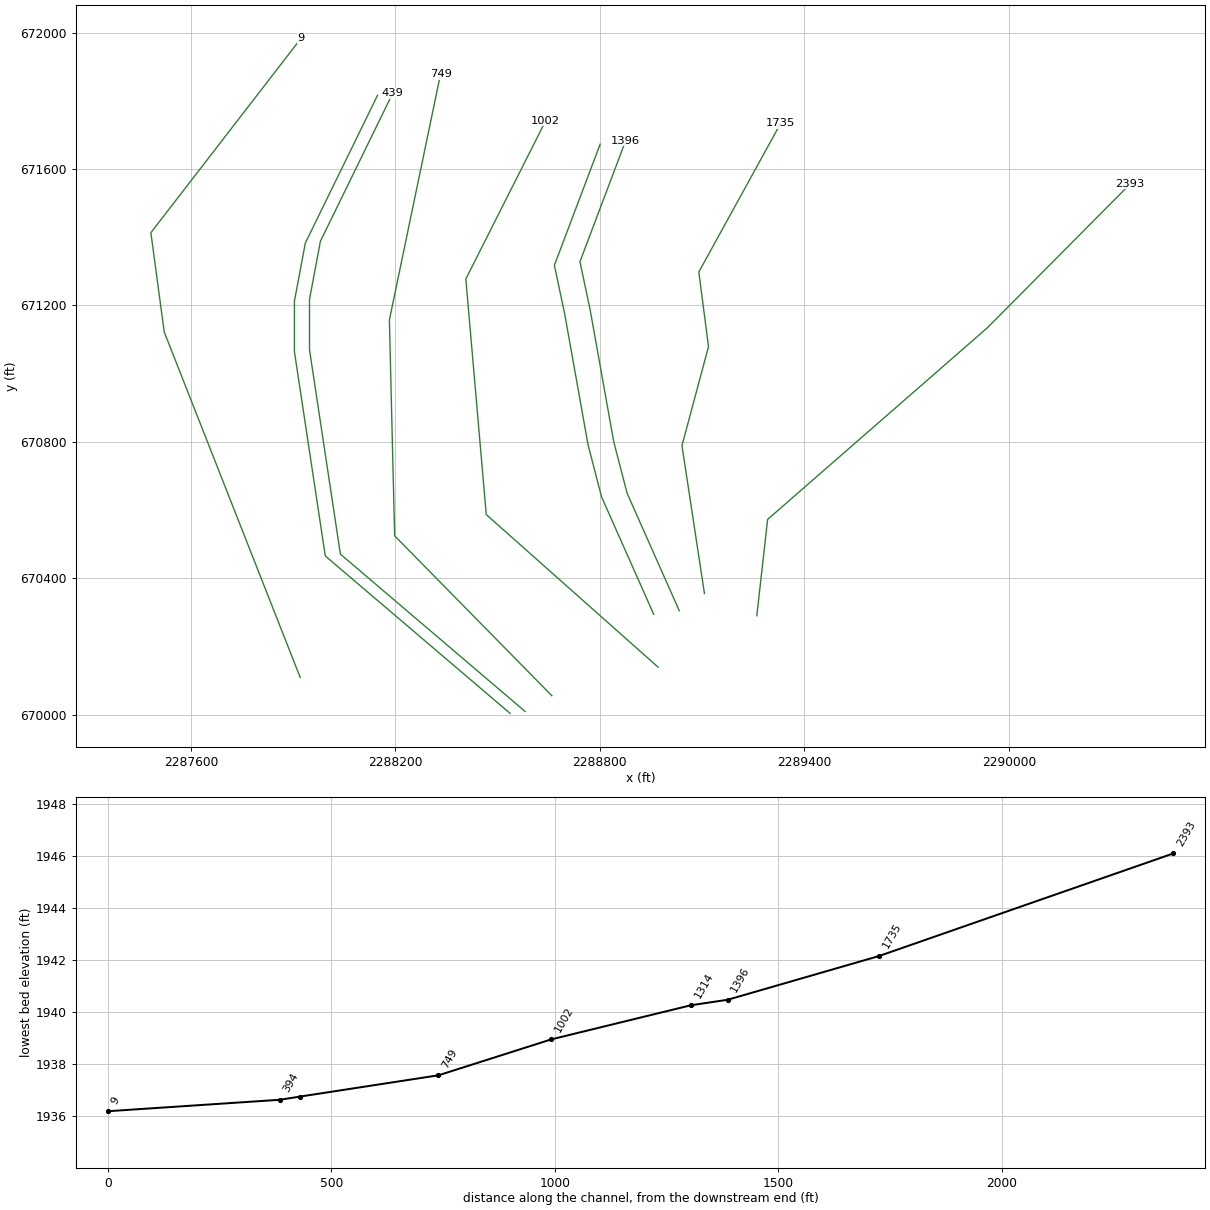
HEC-RAS study FILESCK.prj: FILESCK

--- FILESCK.g01 (geometry) --- (continued)

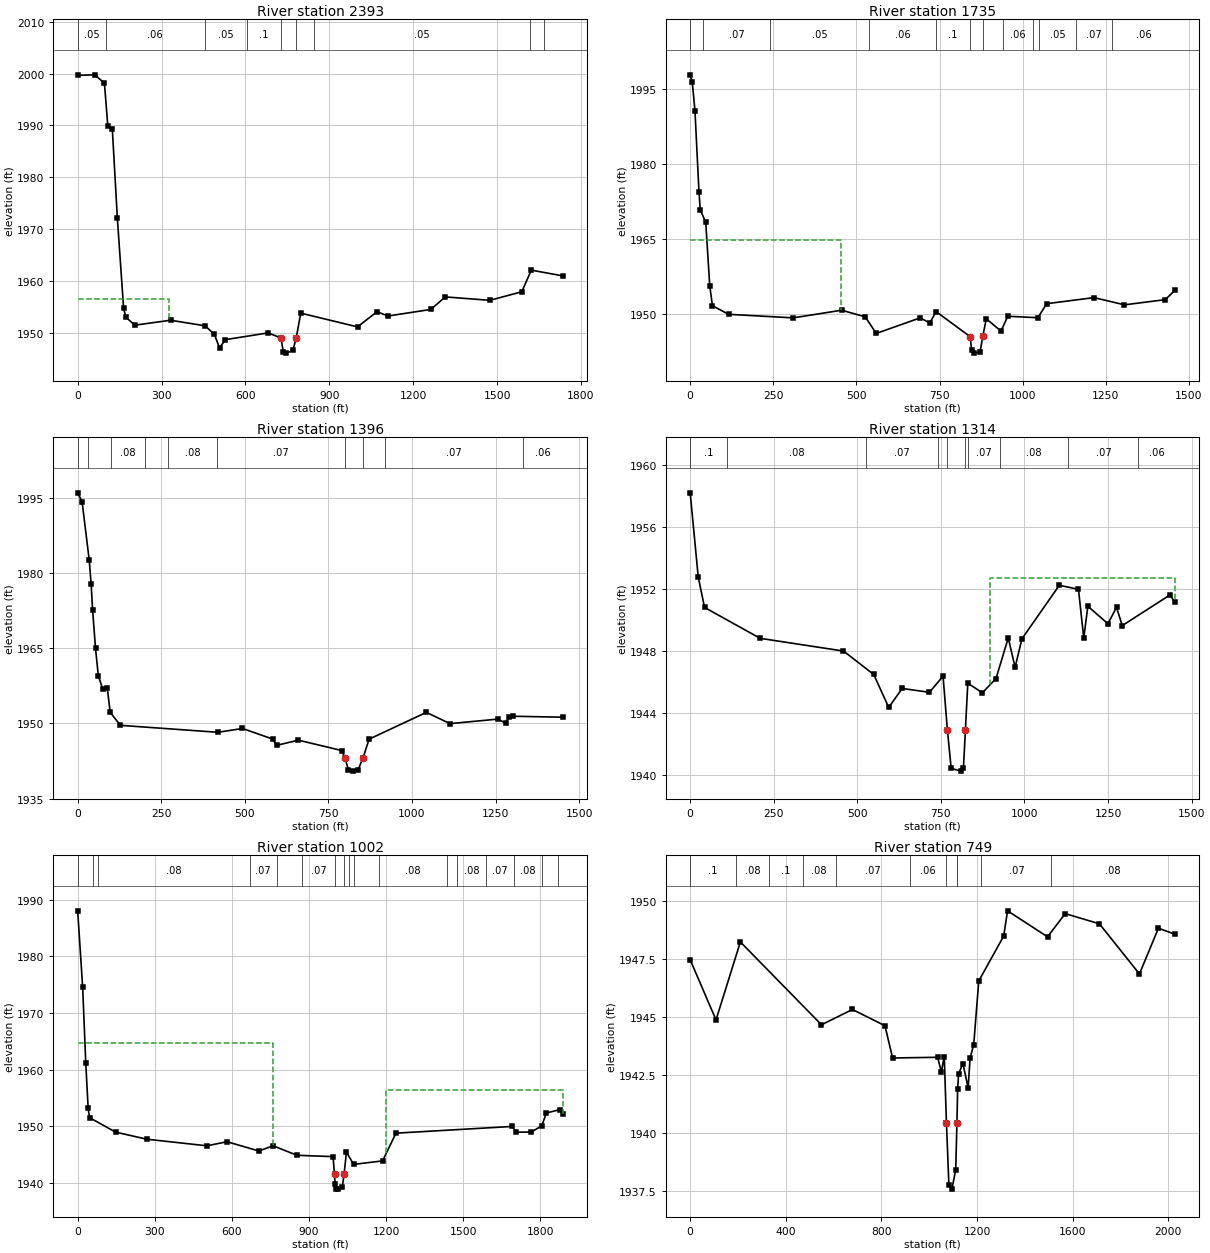
Type RM Length L Ch R = 1 ,2393    ,629.5,658.4,673
XS GIS Cut Line= 4
2289260.33292045670290.0277934992289292.05231541 670572.46640749
2289936.32661702671134.3077980722290355.65841757671556.604089216
#Sta/Elev= 30
       0 1999.65    60.6 1999.75    95.7 1998.15   107.8 1989.93   123.9 1989.35
   141.9 1972.15   164.2 1954.81   172.2 1953.03   204.4 1951.48   332.1 1952.43
   455.7 1951.36   488.9 1949.71   507.3  1947.1   528.5 1948.69   680.9 1949.99
   727.1 1949.02   735.5 1946.29   746.1 1946.09   769.6 1946.61   781.6 1949.01
   797.9  1953.8  1000.9 1951.15  1070.4 1954.07  1109.8 1953.25  1262.6 1954.51
  1314.8 1956.93  1473.8 1956.27  1588.4 1957.92  1622.3 1962.09  1734.2 1960.99
#Mann= 9 ,-1,0
       0     .05       0     100     .06       0  454.21     .05       0
  604.21      .1       0   727.1    .045       0   781.6      .1       0
  844.21     .05       0 1619.06     .06       0 1669.06     .08       0
#XS Ineff= 2 , 0
          326.34  1956.5
Permanent Ineff=
       F       F
Bank Sta=727.1,781.6
XS Rating Curve= 0 ,0
Exp/Cntr=0.3,0.1

Type RM Length L Ch R = 1 ,1735    ,335.8,338.7,334.8
XS GIS Cut Line= 5
 2289106.7280556670354.9535598192289040.77512452670788.833701855
2289118.61270992671079.4943745092289090.20089375671298.170680914
2289330.47453115 671734.70021867
#Sta/Elev= 30
       0 1997.94     6.3 1996.43    14.4 1990.78    26.5  1974.4    30.6 1970.81
    46.8  1968.4    58.9 1955.63      67 1951.65   115.5 1949.93   309.7 1949.22
   455.8 1950.75   526.8 1949.42   559.5 1946.09   691.8 1949.22   720.8  1948.2
   739.8 1950.47   842.3 1945.44   846.3  1942.8   854.1 1942.15     872 1942.37
  879.98 1945.49   890.7 1949.02   935.1 1946.57   955.2 1949.54  1045.9 1949.25
  1072.2 1952.06  1214.8 1953.28  1306.2 1951.83  1428.9 1952.87  1458.6 1954.77
#Mann= 12 ,-1,0
       0     .08       0      40     .07       0     240     .05       0
  538.86     .06       0  738.86      .1       0   842.3    .045       0
  879.98      .1       0  939.77     .06       0 1030.28      .1       0
 1050.28     .05       0 1160.28     .07       0 1270.28     .06       0
#XS Ineff= 2 , 0
          453.76  1964.8
Permanent Ineff=
       F       F
Bank Sta=842.3,879.98
XS Rating Curve= 0 ,0
Exp/Cntr=0.3,0.1

Type RM Length L Ch R = 1 ,1396    ,80.7,81.9,80.9
XS GIS Cut Line= 6
 2289032.9511127670304.3743668182288879.86031599670649.069338208
2288840.42041611670801.1544381692288771.59549868671186.314165665
2288741.51106283671328.4083369072288875.72581375671683.634659999
#Sta/Elev= 30
       0 1995.95    13.3 1994.17    34.5 1982.58    40.3 1977.84    44.6 1972.69
    53.4 1964.94    61.8 1959.47    75.3 1956.77    88.4 1957.14    97.2 1952.21
   127.8  1949.6   419.7 1948.21     493 1948.97   583.1 1946.87   595.3 1945.61
   660.3 1946.64   790.3 1944.57  799.281943.156   810.1  1940.7   822.8 1940.47
   839.1 1940.78  853.871943.154   871.6 1946.84    1043 1952.18  1113.8 1949.94
  1256.6 1950.84  1281.1 1950.02  1289.7 1951.26  1302.5 1951.41  1450.5 1951.22
#Mann= 10 ,-1,0
       0     .08       0      30      .1       0     100     .08       0
     200     .07       0     270     .08       0  417.16     .07       0
  799.28    .045       0  853.87      .1       0  919.65     .07       0
 1330.78     .06       0
Bank Sta=799.28,853.87
XS Rating Curve= 0 ,0
Exp/Cntr(USF)=0,0
Exp/Cntr=0.3,0.1

Type RM Length L Ch R = 1 ,1314    ,314.7,312.3,315.9
XS GIS Cut Line= 6
2288957.96150747670293.8495099432288804.87071076670638.544481333
2288765.43081088670790.6295812952288696.60589345 671175.78930879
 2288666.5214576671317.8834800322288800.73620852671673.109803124
#Sta/Elev= 30
       0  1958.2    24.1 1952.77      43 1950.81   209.4 1948.82   458.6    1948
   549.1 1946.49   593.8 1944.37   634.4 1945.59   715.7 1945.34   756.4 1946.38
  769.331942.922   780.7 1940.44   809.7 1940.26   817.3 1940.43   823.3 1942.92
   830.4 1945.93   874.1 1945.31   914.8 1946.23   951.5 1948.85   971.9 1946.95
   992.4 1948.79  1104.2 1952.24  1161.5 1951.98  1177.3 1948.83  1189.5 1950.89
  1249.6 1949.76  1275.3 1950.82  1292.4 1949.64  1434.6 1951.61  1450.5 1951.15
#Mann= 10 ,-1,0
       0      .1       0     110     .08       0  527.16     .07       0
  741.03     .06       0  769.33    .045       0   823.3     .06       0
  829.65     .07       0  925.54     .08       0 1130.78     .07       0
 1340.78     .06       0
#XS Ineff= 2 , 0
                          896.16         1952.73
Permanent Ineff=
       F       F
Bank Sta=769.33,823.3
XS Rating Curve= 0 ,0
Exp/Cntr(USF)=0,0
Exp/Cntr=0.3,0.1

Type RM Length L Ch R = 1 ,1002    ,253.9,252.5,252.8
XS GIS Cut Line= 4
2288970.71944038 670139.071896442288466.63523876670586.697135173
2288406.73140622 671277.634518162288640.68064319671741.443125474
#Sta/Elev= 30
       0 1988.03    19.5 1974.52    31.6 1961.13    40.8 1953.23    46.2 1951.56
   147.8    1949   269.6 1947.75   503.2 1946.59   581.5 1947.31   704.7 1945.68
   760.9 1946.59   853.3 1944.92   993.8 1944.68  999.631941.563  1001.8  1939.8
  1005.9 1939.02  1013.9 1938.95    1030 1939.39 1036.681941.563    1046 1945.48
    1074 1943.31  1186.5 1943.93  1238.7 1948.82  1689.7    1950  1707.6    1949
  1765.9 1949.02  1806.2 1950.13  1824.1 1952.38  1877.9 1952.98  1887.1 1952.12
#Mann= 17 ,-1,0
       0     .06       0      60     .07       0      80     .08       0
     670     .07       0  774.14     .08       0  874.14     .07       0
  999.63    .045       0 1036.68     .07       0 1054.14     .06       0
 1074.14     .07       0 1174.14     .08       0 1437.67      .1       0
 1477.67     .08       0 1587.67     .07       0 1697.67     .08       0
 1807.67     .06       0 1867.67     .08       0
#XS Ineff= 2 , 0
          760.28 1964.75 1200.43         1956.47
Permanent Ineff=
       F       F
Bank Sta=999.63,1036.68
XS Rating Curve= 0 ,0
Exp/Cntr(USF)=0,0
Exp/Cntr=0.3,0.1

Type RM Length L Ch R = 1 ,749     ,302.4,310.7,308.3
XS GIS Cut Line= 4
2288659.10853207670055.2506931262288197.91541677670524.259466788
2288182.48089136671157.6595411132288332.66200198671879.205684789
#Sta/Elev= 30
       0 1947.45   108.1 1944.86   209.9 1948.22   549.3 1944.65   678.7 1945.31
   814.7 1944.61   846.8 1943.22  1034.8 1943.25  1050.6 1942.63  1062.8 1943.28
 1072.041940.408  1082.2 1937.75  1094.8 1937.57  1110.8 1938.41 1115.76 1940.41
  1118.8 1941.89  1122.8 1942.54  1140.9 1942.98  1162.8 1941.93  1170.8 1943.22
    1186 1943.79  1207.2 1946.54  1311.3 1948.47  1327.6 1949.56  1494.9 1948.44
  1568.7 1949.44  1711.9    1949  1879.2 1946.84  1958.6 1948.81  2028.4 1948.55
#Mann= 11 ,-1,0
       0      .1       0     190     .08       0     330      .1       0
     470     .08       0     610     .07       0  917.78     .06       0
 1072.04    .045       0 1115.76     .06       0 1117.78     .08       0
 1217.78     .07       0 1511.36     .08       0
Bank Sta=1072.04,1115.76
XS Rating Curve= 0 ,0
Exp/Cntr(USF)=0,0
Exp/Cntr=0.3,0.1

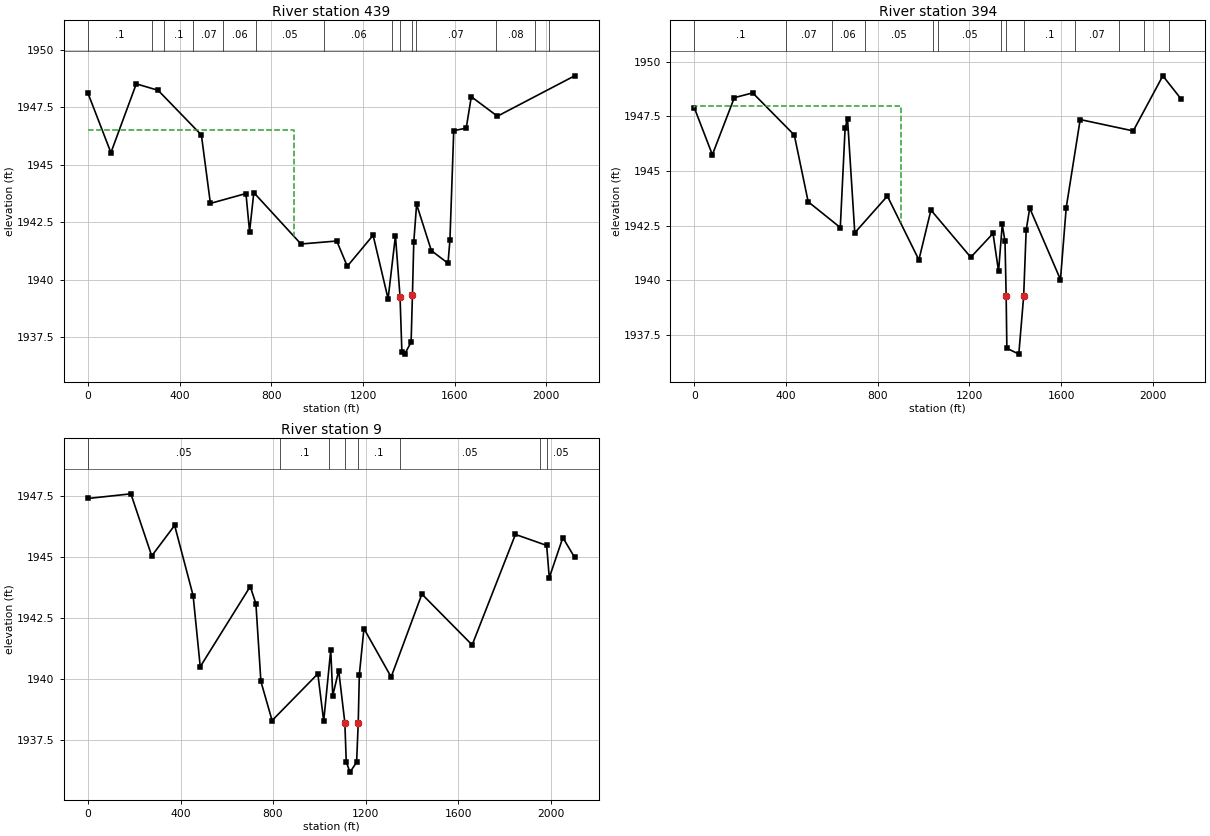
Type RM Length L Ch R = 1 ,439     ,44.9,44.3,45.3
XS GIS Cut Line= 6
2288580.87008373670008.8933174662288038.76388805670470.640483957
2287948.18328466671069.9557593712287948.18328466671217.961559173
2287980.15253741671388.4642405442288192.10561433671822.139589833
#Sta/Elev= 30
       0 1948.12     100 1945.53   210.7 1948.53   305.7 1948.25   494.8  1946.3
   534.1 1943.32   689.2 1943.75     705 1942.09   723.5 1943.79   929.3 1941.55
  1085.4 1941.68  1131.4 1940.58    1244 1941.93  1309.4 1939.16  1341.5 1941.91
 1361.55 1939.25  1369.6 1936.84  1381.7 1936.75  1409.8 1937.27 1415.611939.307
  1421.4 1941.62  1433.8 1943.28  1498.2 1941.26  1570.9 1940.71  1579.3 1941.74
  1595.9 1946.49  1650.3  1946.6  1672.5 1947.97  1786.4 1947.12  2123.3 1948.88
#Mann= 14 ,-1,0
       0      .1       0     280     .08       0     330      .1       0
     460     .07       0     590     .06       0   732.1     .05       0
 1031.02     .06       0 1328.25      .1       0 1361.55    .045       0
 1415.61      .1       0 1431.89     .07       0 1780.56     .08       0
 1950.56     .07       0 2010.56     .08       0
#XS Ineff= 2 , 0
             900 1946.54
Permanent Ineff=
       F       F
Bank Sta=1361.55,1415.61
XS Rating Curve= 0 ,0
Exp/Cntr(USF)=0,0
Exp/Cntr=0.3,0.1

Type RM Length L Ch R = 1 ,394     ,383.2,384.9,390.5
XS GIS Cut Line= 6
2288536.58947174670003.4553475722287994.48327606670465.202514063
2287903.90267266671064.5177894772287903.90267266671212.523589279
2287935.87192542 671383.026270652288147.82500234671816.701619939
#Sta/Elev= 30
       0 1947.88    78.1 1945.75   173.9 1948.36   254.1 1948.58   435.7 1946.65
   496.2  1943.6   636.3 1942.42   657.3 1946.96   667.8  1947.4   699.5 1942.18
   841.7 1943.86   979.3 1940.94  1031.8 1943.22  1205.6 1941.06  1302.7 1942.15
  1326.9 1940.42    1343 1942.56    1355 1941.79 1360.061939.273  1363.1  1936.9
  1415.2 1936.63 1436.391939.277  1447.3 1942.29  1462.8 1943.31    1597 1940.04
  1622.1 1943.33    1683 1947.36  1914.5 1946.84  2043.7 1949.36  2123.3  1948.3
#Mann= 13 ,-1,0
       0      .1       0     400     .07       0     600     .06       0
   742.1     .05       0 1041.02     .06       0 1061.02     .05       0
 1338.25      .1       0 1360.06    .045       0 1436.39      .1       0
 1660.56     .07       0 1850.56     .08       0 1960.56     .07       0
 2070.56     .08       0
#XS Ineff= 2 , 0
             900 1947.97
Permanent Ineff=
       F       F
Bank Sta=1360.06,1436.39
XS Rating Curve= 0 ,0
Exp/Cntr(USF)=0,0
Exp/Cntr=0.3,0.1

Type RM Length L Ch R = 1 ,9       ,,,
XS GIS Cut Line= 4
2287920.93455914670108.6886957352287521.97748081671122.312084777
2287482.82642125671413.4980902352287923.27584127671983.635395039
#Sta/Elev= 30
       0 1947.38   185.4 1947.57   275.5 1945.03   374.5 1946.28   454.4 1943.41
   485.2  1940.5   701.3 1943.78   725.8 1943.08   747.4  1939.9   795.8  1938.3
   993.5 1940.21  1018.9 1938.28  1049.4 1941.18    1058 1939.32  1083.8 1940.34
 1110.331938.212  1116.4 1936.61  1132.5 1936.19  1161.1 1936.59 1168.221938.209
  1172.9 1940.17  1192.9 1942.06  1310.5 1940.08  1443.4 1943.47  1660.7 1941.39
  1847.7 1945.91  1982.7 1945.46  1994.1 1944.14  2052.7 1945.78  2103.6 1944.97
#Mann= 8 ,-1,0
       0     .05       0     830      .1       0    1040    .025       0
 1110.33    .045       0 1168.22      .1       0 1349.31     .05       0
 1953.12     .06       0 1983.12     .05       0
Bank Sta=1110.33,1168.22
XS Rating Curve= 0 ,0
Exp/Cntr(USF)=0,0
Exp/Cntr=0.3,0.1
LCMann Table=0

Chan Stop Cuts=-1
Use User Specified Reach Order=0
Composite Channel Slope=5